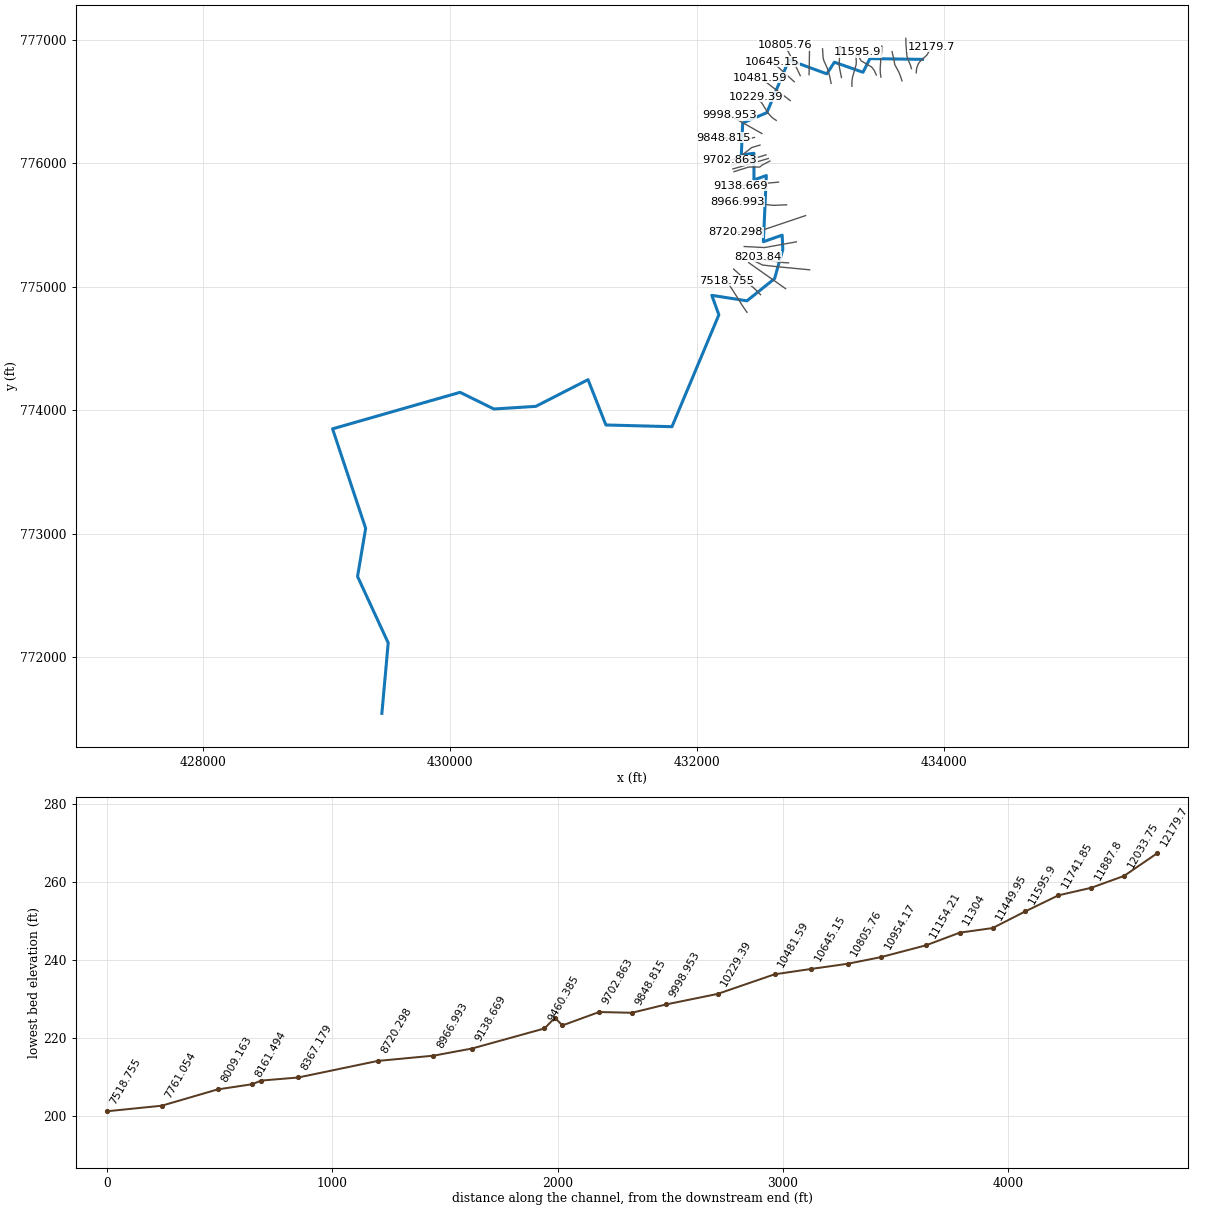
--- 2986_ras.prj (project) ---

Proj Title=2986
Current Plan=p01
Default Exp/Contr=0.3,0.1
English Units
Geom File=g01
Flow File=f01
Plan File=p01
Y Axis Title=Elevation
X Axis Title(PF)=Main Channel Distance
X Axis Title(XS)=Station
BEGIN DESCRIPTION:
RFD model 2986 exported to HEC-RAS
END DESCRIPTION:

--- 2986_ras.p01 (plan) ---

Plan Title=Plan 01
Program Version=4.10
Short Identifier=Plan 01
Geom File=g01
Flow File=f01
Subcritical Flow
Calc Critical at every XS
Secant Critical Depth

--- 2986_ras.f01 (steady flow) ---

Flow Title=Flow 01
Program Version=5.01
Number of Profiles= 6
Profile Names=10yr,25yr,50yr,100yr,100plus,500yr
River Rch & RM=2986,38, 12179.7
  149.12  240.88  327.16  406.99  594.21 1062.09
River Rch & RM=2986,38,12033.75
  150.24  242.73  329.71   410.2  598.89 1069.49
River Rch & RM=2986,38, 11887.8
  157.25  254.32   345.7  430.35  628.31 1115.86
River Rch & RM=2986,38,11741.85
  157.98  255.52  347.36  432.45  631.38  1120.7
River Rch & RM=2986,38, 11595.9
  169.22  274.13  373.06  464.85  678.68 1194.66
River Rch & RM=2986,38,11449.95
  170.64  276.49  376.33  468.98   684.7 1204.07
River Rch & RM=2986,38,   11304
  173.96  281.94  383.82  478.38  698.43 1225.14
River Rch & RM=2986,38,11154.21
   178.9  290.14  395.17  492.71  719.36 1257.64
River Rch & RM=2986,38,10954.17
  183.13  297.16  404.87  504.96  737.24 1285.23
River Rch & RM=2986,38,10805.76
  184.18   298.9  407.28     508  741.68 1292.09
River Rch & RM=2986,38,10645.15
  200.53  326.01  444.77  555.32  810.77 1397.82
River Rch & RM=2986,38,10229.39
  206.26  335.57  458.04  572.12  835.29 1435.29
River Rch & RM=2986,38,9998.953
  222.51  362.85  496.08  620.46  905.87 1543.34
River Rch & RM=2986,38,9848.815
  226.35  369.31  505.09  631.92  922.61 1568.83
River Rch & RM=2986,38,9702.863
  228.27  372.54  509.59  637.65  930.97 1581.52
River Rch & RM=2986,38,9138.669
  236.51   386.4  528.94  662.27  966.92 1636.03
River Rch & RM=2986,38,8966.993
  237.45  387.99  531.16   665.1  971.05 1642.27
River Rch & RM=2986,38,8720.298
   243.9  398.92  546.48  684.66   999.6 1685.72
River Rch & RM=2986,38,8367.179
  264.74  433.82  595.07  746.34 1089.66 1819.52
River Rch & RM=2986,38,8009.163
   268.3  439.87  603.57  757.22 1105.54 1843.43
River Rch & RM=2986,38,7518.755
  270.95  444.38  609.91  765.34  1117.4 1861.28
River Rch & RM=2986,38,7246.323
  280.03  459.84  631.65  793.19 1158.05 1922.27
River Rch & RM=2986,38,7028.273
  281.49  462.32  635.14  797.66 1164.58 1932.03
River Rch & RM=2986,38, 6783.05
  284.69  467.77  642.81  807.47 1178.91 1953.45
River Rch & RM=2986,38,6537.827
  288.75  474.68  652.54  819.93  1197.1 1980.57
River Rch & RM=2986,38,6292.605
  291.36  479.12  658.77  827.92 1208.77 1997.93
River Rch & RM=2986,38,6047.382
  293.05  482.03  662.88   833.2 1216.47 2009.47
Boundary for River Rch & Prof#=2986,38,1
Up Type= 0
Dn Type= 2
Boundary for River Rch & Prof#=2986,38,2
Up Type= 0
Dn Type= 2
Boundary for River Rch & Prof#=2986,38,2
Up Type= 0
Dn Type= 2
Boundary for River Rch & Prof#=2986,38,2
Up Type= 0
Dn Type= 2
Boundary for River Rch & Prof#=2986,38,2
Up Type= 0
Dn Type= 2
Boundary for River Rch & Prof#=2986,38,2
Up Type= 0
Dn Type= 2

--- 2986_ras.g01 (geometry) ---

Geom Title=2986
Program Version=4.10

River Reach=2986,38
Reach XY= 30
433829.655412793 776840.42869556433402.988746136776846.539806709
433346.877635121776735.984251142433115.210968435776817.650917858
433054.099857241776723.206473351432746.877635002776835.428695634
432567.988746107776408.762028918432372.433190554776324.873139992
432361.395764053776065.656882346432463.544301778776079.873140037
432463.544301778775863.762028977 432564.09985733775899.873140007
432540.210968345775363.762028918432692.433190554775416.539806724
432697.433190554775300.428695619432630.766524017  775064.3175845
432406.877635092774884.873140067432122.433190644 774929.31758447
432179.655413002774771.539806709431799.655412793773865.428695589
431264.655412793773879.317584485431119.933190554774246.262028962
430696.599857241774030.012028933430357.849857241774008.762028977
430083.683190554774143.762028918429050.867060542773848.036888927
429318.830628186773042.467150852429253.240577221772652.174289212
429501.381593376772114.685790658429450.357376039771543.508802161

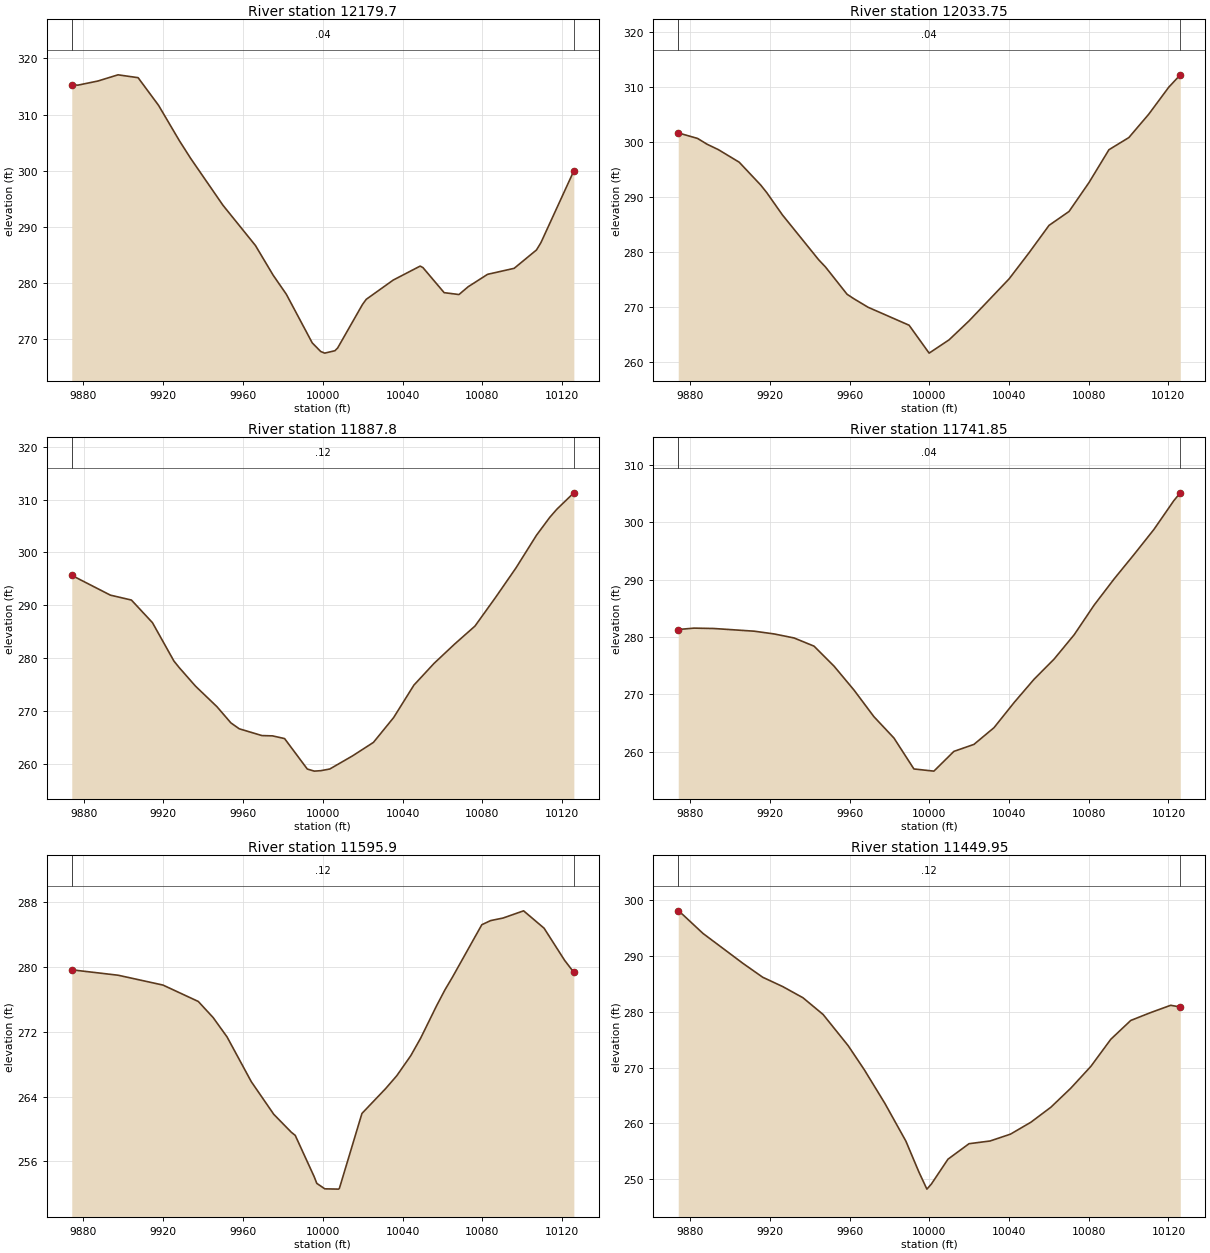
Type RM Length L Ch R = 1 , 12179.7,145.951600,145.951600,145.951600
XS GIS Cut Line= 6
433777.587200613776731.959686421433781.935857299776769.787897422
433795.167351189776805.082388884433812.255374665776827.460839865
433864.346274834776875.167588328433902.444605304776941.721430654
#Sta/Elev= 30
9874.196315.32199877.256 315.2419887.322315.98059897.388317.08489907.454316.5754
9917.717311.63349928.161305.31589933.856302.13999949.984 293.8079966.277286.6194
9975.136281.33169981.792277.89869994.764269.2301    9999267.6956   10001267.4072
10006.11267.835310007.49268.325310019.89276.063110021.82277.010110035.34280.4468
10048.86282.942910050.26282.670710060.89278.199310068.31 277.86610072.91 279.254
10082.65 281.47310095.97282.542410107.17285.822610109.39287.1221 10125.9299.9409
#Mann= 3 , 0 , 0
9874.196    0.04       09874.196    0.04       0 10125.9    0.04       0
#XS Ineff= 2 , 0
       0                               0
Bank Sta=9874.196,10125.9
Exp/Cntr=0.3,0.1

Type RM Length L Ch R = 1 ,12033.75,145.951600,145.951600,145.951600
XS GIS Cut Line= 6
433739.145491261776765.736294883433730.748506171776793.945041892
433708.229518524776848.153577113433702.655625786776866.974843169
433695.188189843776959.242796781433693.710152821  777010.8018157
#Sta/Elev= 27
9874.065   301.79883.731300.69879888.596 299.6289894.164298.6621 9904.64296.3745
9915.468292.20599918.482290.83799926.297286.80299944.549278.61229947.954277.3077
9958.782272.34479962.197271.52969969.338269.97989989.902266.7117 9999.96261.6367
10009.99264.061510020.01267.509810040.07275.1399 10050.1   279.910060.12284.8771
10070.15287.406210080.17292.665110090.17298.635910100.17  300.8510110.18305.1147
10120.18310.008210125.99312.2647
#Mann= 3 , 0 , 0
9874.065    0.04       09874.065    0.04       010125.99    0.04       0
#XS Ineff= 2 , 0
       0                               0
Bank Sta=9874.065,10125.99
Exp/Cntr=0.3,0.1

Type RM Length L Ch R = 1 , 11887.8,145.951600,145.951600,145.951600
XS GIS Cut Line= 6
433662.799868217776666.600776275433650.367184076776704.170324041
433636.451143572776738.664045036433604.477888836776797.858154674
433597.439685265776838.445694746433582.239256198776903.272612035
#Sta/Elev= 30
9874.063295.66789893.443291.92039903.977290.99359914.531286.71049925.314279.4344
9927.982278.18679936.097274.6949 9946.88270.79159953.867 267.7289958.044266.6087
9969.429  265.329974.788265.26139980.814264.74939992.199258.9825 9995.71258.5845
    9999258.669910003.47 258.98510014.87 261.46710025.37264.024310035.52268.7334
10045.67274.874410055.82279.008910066.05282.634110076.32286.066610086.59291.4659
10096.86 297.07110107.13303.249910113.81306.6555 10117.4308.2057 10125.9311.3026
#Mann= 3 , 0 , 0
9874.063    0.12       09874.063    0.12       0 10125.9    0.12       0
#XS Ineff= 2 , 0
       0                               0
Bank Sta=9874.063,10125.9
Exp/Cntr=0.3,0.1

Type RM Length L Ch R = 1 ,11741.85,145.951600,145.951600,145.951600
XS GIS Cut Line= 6
433491.778251424776697.160695417433487.035979155 776734.98256029
433486.145632755776767.886116619433490.897394769776833.349670621
433498.223711525776901.085586516433499.761630294776948.209923014
#Sta/Elev= 26
9874.032281.31699881.933281.55989892.011281.49129912.167281.02559922.171280.5445
9932.175279.84519942.178278.41939952.197274.94389962.223 270.7749972.248266.1224
9982.274262.41629992.299257.022510002.33256.645310012.36260.085510022.42261.3029
10032.48264.211810042.54268.580210052.59272.651310062.65276.164810072.71280.3988
10082.75285.577110092.75290.123710102.76294.388110112.76298.763510122.77303.7878
10125.98305.1309
#Mann= 3 , 0 , 0
9874.032    0.04       09874.032    0.04       010125.98    0.04       0
#XS Ineff= 2 , 0
       0                               0
Bank Sta=9874.032,10125.98
Exp/Cntr=0.3,0.1

Type RM Length L Ch R = 1 , 11595.9,145.951600,145.951600,145.951600
XS GIS Cut Line= 6
 433454.89034422776713.829121098433438.085617799 776750.51274528
433416.620321301776778.701312969433331.969526985776828.512504315
433314.371087486776860.446828335433304.949533049776899.490581451
#Sta/Elev= 30
9874.147279.66599897.433278.99489919.857277.78149937.579275.75179945.037273.7583
9952.008271.36489964.166265.83049975.432 261.7979984.192259.58829986.189259.1927
9995.601 254.1329997.009253.2576   10001252.585510007.93252.548510008.35252.6639
10019.63261.905910031.55264.989710037.13266.583110044.11269.047710049.09271.2283
   10057275.194810061.26277.196310064.99278.748410079.73285.241610084.17285.7532
10090.39286.068310100.68 286.95910110.96 284.80710121.25280.836810125.87279.3501
#Mann= 3 , 0 , 0
9874.147    0.12       09874.147    0.12       010125.87    0.12       0
#XS Ineff= 2 , 0
       0                               0
Bank Sta=9874.147,10125.87
Exp/Cntr=0.3,0.1

Type RM Length L Ch R = 1 ,11449.95,145.951600,145.951600,145.951600
XS GIS Cut Line= 6
433257.110533812776622.622283066433257.564607022776663.741421029
433261.831301696776694.831031751433291.539469545776798.880466842
433292.622378666776823.870757449 433289.76666343 776869.80161626
#Sta/Elev= 28
9874.063298.06119876.441297.35359886.441294.02899906.443288.67799916.455286.1696
9926.549284.49189936.642282.5014 9946.74279.51029959.316273.92499967.388269.6276
9977.712 263.6119988.253256.85059994.804251.31179998.809248.2487   10001249.1356
10009.39253.609210019.94256.378410030.48256.862210040.73258.087510050.94260.2134
10061.03 262.91710071.04 266.32910081.05270.212110091.07275.070610101.09278.4413
10111.11279.854110121.13281.154310125.94280.8433
#Mann= 3 , 0 , 0
9874.063    0.12       09874.063    0.12       010125.94    0.12       0
#XS Ineff= 2 , 0
       0                               0
Bank Sta=9874.063,10125.94
Exp/Cntr=0.3,0.1

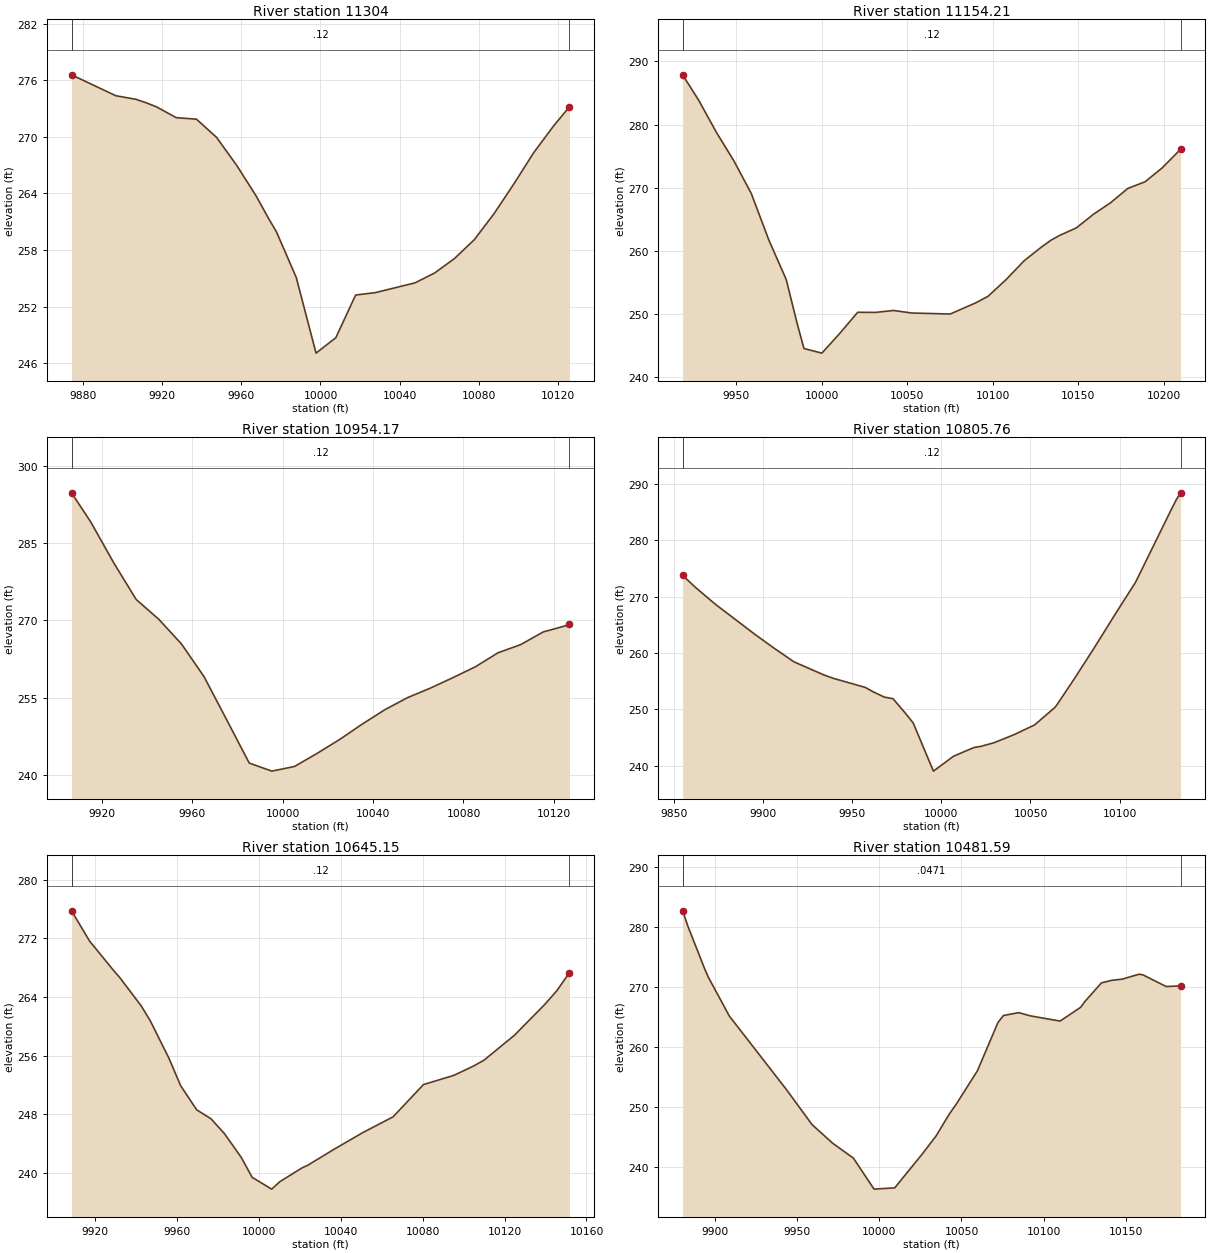
Type RM Length L Ch R = 1 ,   11304,149.785500,149.785500,149.785500
XS GIS Cut Line= 6
433172.477604412776693.036135913433156.573990461776771.841019197
433154.219023594776791.095708457433154.750580708776816.244742961
 433154.81950526 776818.24355496433161.173899427776943.048589662
#Sta/Elev= 26
9874.054 276.584 9896.46274.36659906.662 273.9879911.853273.61659916.863273.2028
9927.065272.03979937.267271.88079947.468 269.939 9957.63266.97639967.412263.7497
9973.845261.31399977.751259.92219987.753255.08469997.755247.068810007.77248.7051
10017.78253.229510027.79253.486610047.82254.520810057.83255.574910067.84257.1072
10077.86259.106310087.87261.873210097.88265.026610107.89268.327810117.91271.1547
10125.97273.1959
#Mann= 3 , 0 , 0
9874.054    0.12       09874.054    0.12       010125.97    0.12       0
#XS Ineff= 2 , 0
       0                               0
Bank Sta=9874.054,10125.97
Exp/Cntr=0.3,0.1

Type RM Length L Ch R = 1 ,11154.21,200.035500,200.035500,200.035500
XS GIS Cut Line= 6
433088.936198592776645.712879926433075.582515925776709.309590876
433057.180326879776770.095604762433028.732611835776833.096819818
433023.623495728776856.711171463433019.399383187776925.758397326
#Sta/Elev= 30
9918.719287.86749928.209283.80199938.427278.77919948.645274.27389958.863269.0874
9969.081261.75729979.299  255.469985.663248.53429989.663244.548610000.14  243.82
10010.61246.946610021.08250.282310031.56250.266410042.03250.571710052.76250.1665
 10075.2250.011510090.22251.790310097.25252.807810107.89255.467910118.45258.4515
10128.68260.641210134.15261.702410138.91262.415810148.97263.649310158.99  265.81
10169.01267.637710179.02269.886510189.04270.931910199.06273.123410209.84 276.074
#Mann= 3 , 0 , 0
9918.719    0.12       09918.719    0.12       010209.84    0.12       0
#XS Ineff= 2 , 0
       0                               0
Bank Sta=9918.719,10209.84
Exp/Cntr=0.3,0.1

Type RM Length L Ch R = 1 ,10954.17,148.418100,148.418100,148.418100
XS GIS Cut Line= 2
432910.168378138  776716.4286022432914.147647106776936.609091785
#Sta/Elev= 24
9906.661294.74729915.234289.03739925.236281.23489935.237274.07159945.239270.2304
9955.241265.46339965.242259.12659975.244250.77099985.245242.35719995.247240.7907
10005.25241.689110015.25244.224310025.25246.928510035.25249.915410045.26252.7043
10055.26255.036510065.26256.861710075.26258.894210085.26261.014110095.26263.7329
10105.27265.309710115.27267.774610125.27268.982910126.88269.2599
#Mann= 3 , 0 , 0
9906.661    0.12       09906.661    0.12       010126.88    0.12       0
#XS Ineff= 2 , 0
       0                               0
Bank Sta=9906.661,10126.88
Exp/Cntr=0.3,0.1

Type RM Length L Ch R = 1 ,10805.76,160.603600,160.603600,160.603600
XS GIS Cut Line= 3
  432838.8330158776708.524307564432790.449730396776810.741036206
432712.324730396776957.225411221
#Sta/Elev= 30
9855.018273.74739862.183271.63469873.247268.66399895.374263.33979906.438260.8177
9917.501258.42549934.098256.12779939.629 255.5019957.472253.89829961.756253.1365
9968.108252.18699972.935251.91049979.688249.41249984.268 247.6059995.601239.0756
10006.93241.724410018.27243.249110022.19243.4649 10029.6244.105410040.93245.5542
10052.27247.2481 10063.6 250.32710064.69250.750810074.93255.593610085.94261.0087
 10097.6266.922910108.93272.544710128.44285.0891 10131.6287.068910134.12 288.372
#Mann= 3 , 0 , 0
9855.018    0.12       09855.018    0.12       010134.12    0.12       0
#XS Ineff= 2 , 0
       0                               0
Bank Sta=9855.018,10134.12
Exp/Cntr=0.3,0.1

Type RM Length L Ch R = 1 ,10645.15,163.560600,163.560600,163.560600
XS GIS Cut Line= 2
432790.160378546776659.048327893432610.472878546776823.110827893
#Sta/Elev= 28
9908.357275.75759917.184271.62599928.886267.61969932.015266.61339942.428262.7684
9946.846260.73749955.969255.62519961.677 251.887 9969.51248.59299976.508247.3688
9983.051245.35199991.339242.07969996.593239.384510006.17237.768110010.13238.7839
   10021240.669310023.67 241.00810037.22 243.30310050.76245.493410065.49247.6358
10080.32252.038210095.15253.293210104.92254.584210109.99255.382610124.82258.7795
10139.65262.990210145.55264.860910151.68267.3299
#Mann= 3 , 0 , 0
9908.357    0.12       09908.357    0.12       010151.68    0.12       0
#XS Ineff= 2 , 0
       0                               0
Bank Sta=9908.357,10151.68
Exp/Cntr=0.3,0.1

Type RM Length L Ch R = 1 ,10481.59,252.206900,252.206900,252.206900
XS GIS Cut Line= 2
432757.608295212776506.704577873432516.722878555776690.298327888
#Sta/Elev= 30
 9880.38282.7362 9883.66280.11719894.065272.88059896.233271.56939908.806265.2027
9943.556 252.946  9959.1247.12419971.673244.01259984.247241.5417 9996.82 236.371
10009.39236.581310026.04 242.18210034.54245.222410042.54  248.8510047.11250.6468
10059.69256.081610072.26264.161910075.53265.290610084.83265.776210092.03265.2297
10109.98264.369710122.55266.672910125.02 267.60510135.13270.729510141.52271.1638
 10147.7271.347810158.02272.175810160.27 272.08310174.51270.126210183.25270.2259
#Mann= 3 , 0 , 0
 9880.38  0.0471       0 9880.38  0.0471       010183.25  0.0471       0
#XS Ineff= 2 , 0
       0                               0
Bank Sta=9880.38,10183.25
Exp/Cntr=0.3,0.1

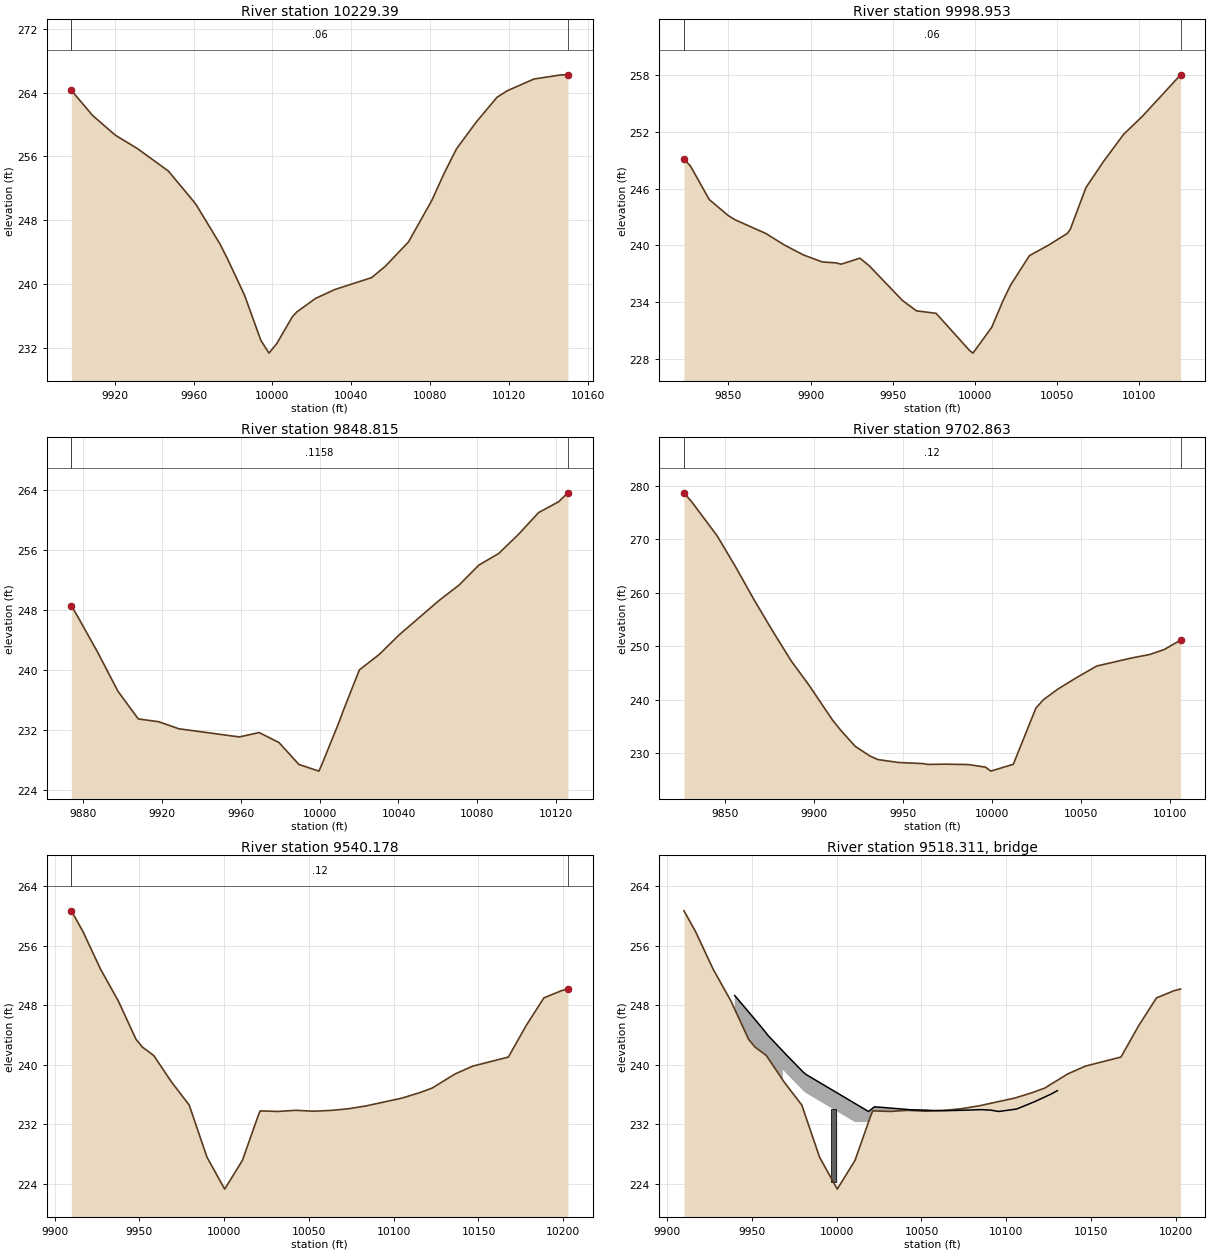
Type RM Length L Ch R = 1 ,10229.39,230.432200,230.432200,230.432200
XS GIS Cut Line= 6
432644.040233064776346.211999938432612.592290622776367.909828663
432589.725096179776391.476098884432570.231929918776418.189118483
 432527.48379959776486.828477226432484.316979126776537.786975804
#Sta/Elev= 30
9898.034264.28639908.647261.17729918.094259.13839920.571258.62949931.564256.9826
9947.201254.17899960.112250.35129961.561249.86559973.499244.99279977.152243.2013
9985.878238.60719994.116  232.979998.257231.354210002.21232.553710010.16 235.928
10012.33236.507810021.84238.205610031.65239.326110050.34240.818110057.24242.2344
10069.03245.292210080.91250.525510087.13253.904610093.42256.979210103.44260.3275
10113.89263.413110119.22264.248210132.61265.700210146.14 266.21910149.91266.2297
#Mann= 3 , 0 , 0
9898.034    0.06       09898.034    0.06       010149.91    0.06       0
#XS Ineff= 2 , 0
       0                               0
Bank Sta=9898.034,10149.91
Exp/Cntr=0.3,0.1

Type RM Length L Ch R = 1 ,9998.953,150.137800,150.137800,150.137800
XS GIS Cut Line= 2
432528.441628546776239.777494565432264.761549979776387.917524606
#Sta/Elev= 30
9822.931249.12939826.879248.37789838.349244.83679849.819243.16379854.009242.7086
9872.759241.26159884.229240.03049895.699238.99519907.169238.25479915.258238.1615
 9918.64238.0192 9930.11238.65479935.674237.8636 9956.09234.1758 9964.52233.0969
9976.506232.83159996.922228.8994 9998.93228.6323 10010.4 231.36710017.34234.2059
10021.87235.817310033.34238.925410044.81240.013910056.28241.251810058.17241.6872
10067.75246.108410078.59248.890510090.69251.720810102.16253.633510125.38258.0028
#Mann= 3 , 0 , 0
9822.931    0.06       09822.931    0.06       010125.38    0.06       0
#XS Ineff= 2 , 0
       0                               0
Bank Sta=9822.931,10125.38
Exp/Cntr=0.3,0.1

Type RM Length L Ch R = 1 ,9848.815,145.951600,145.951600,145.951600
XS GIS Cut Line= 6
432467.883750015776208.390998586432398.978406378776190.939437837
432352.084894032776185.329618967 432345.56227093776186.173522354
432333.339216858776189.600980347432220.235475572776205.517410524
#Sta/Elev= 26
9874.114248.54399877.089247.24619887.405242.3871 9897.72237.17199908.036233.4709
9918.352233.09939928.668232.15569959.273  231.079969.345231.65339979.416230.3191
9989.487227.40059999.626226.5077   10001227.300310010.02233.160510011.73234.3953
10020.15240.014310030.25242.076310040.35244.690810060.55249.271910070.65251.3158
10080.75253.990610090.84255.548410100.94258.115410111.04260.999210121.14262.4361
10125.95263.6353
#Mann= 3 , 0 , 0
9874.114  0.1158       09874.114  0.1158       010125.95  0.1158       0
#XS Ineff= 2 , 0
       0                               0
Bank Sta=9874.114,10125.95
Exp/Cntr=0.3,0.1

Type RM Length L Ch R = 1 ,9702.863,162.685400,162.685400,162.685400
XS GIS Cut Line= 4
 432512.78589204776146.206655279432445.424780965776126.067766368
432337.091447592776041.345544159432268.341447592776022.595544159
#Sta/Elev= 30
9826.694278.69149830.907277.07339845.258270.70089855.695 264.8719866.133258.6925
 9876.57252.85549887.007247.26939897.001242.74979910.236236.21829914.968234.2739
 9922.93231.3343  9931.2229.53099935.625 228.8649947.433228.31019961.015228.1152
9963.666 227.956 9973.71227.99739986.405227.93559996.132227.4479  9999.1226.7009
10011.79227.980710024.49238.4832 10028.6 240.005 10036.7242.003610047.06244.1146
10058.65 246.33510078.16247.830210088.52248.496310096.65249.422710105.79251.1805
#Mann= 3 , 0 , 0
9826.694    0.12       09826.694    0.12       010105.79    0.12       0
#XS Ineff= 2 , 0
       0                               0
Bank Sta=9826.694,10105.79
Exp/Cntr=0.3,0.1

Type RM Length L Ch R = 1 ,9540.178,33.944600,33.944600,33.944600
XS GIS Cut Line= 2
432561.459560722776067.242968649432281.392889269775981.550927373
#Sta/Elev= 30
9909.916260.68589916.671257.93479927.129 252.8429937.587248.57799948.044243.4117
9951.761242.37999958.502241.23119968.959237.68369979.417234.57289989.875227.5773
10000.33223.272610010.79227.136710020.12233.167410021.25233.789210031.71233.7159
10042.16233.867310052.62233.746110063.08 233.85410073.54234.082910083.99 234.474
10104.91235.509510115.37236.244910122.65236.854410136.28238.766210146.74239.8148
10167.65241.027710178.11245.254910188.57248.979610199.03 249.956 10202.8250.1727
#Mann= 3 , 0 , 0
9909.916    0.12       09909.916    0.12       0 10202.8    0.12       0
#XS Ineff= 2 , 0
       0                10017.43       0
Bank Sta=9909.916,10202.8
Exp/Cntr=0.3,0.1

Type RM Length L Ch R = 3 ,9518.311,,,
BEGIN DESCRIPTION:
END DESCRIPTION:
Bridge Culvert--1,0,-1,-1, 0
Deck Dist Width WeirC Skew NumUp NumDn MinLoCord MaxHiCord MaxSubmerge Is_Ogee
9.662300,14.620000,2.6,0, 28, 28, , , 0.95, 0, 0,0,,
 9939.85 9948.99 9956.14 9959.46 9968.22 9968.22 9969.93 9980.40 9981.9610018.74
10022.2910023.5010027.8610027.8610032.7710043.2410053.7110057.1810064.1810074.66
10085.1310090.8610095.6010106.0710116.5410124.5310127.0210130.13
  249.30  246.84  244.90  243.94  241.83  241.83  241.41  238.97  238.68  233.71
  234.34  234.32  234.24  234.24  234.15  233.95  233.88  233.84  233.82  233.88
  233.96  233.89  233.71  234.04  235.01  235.85  236.12  236.51
 -750.70 -753.16 -755.10 -756.06 -758.17  239.33  238.91  236.47  236.18  231.21
  231.84  231.82  231.74 -765.76 -765.85 -766.05 -766.12 -766.16 -766.18 -766.12
 -766.04 -766.11 -766.29 -765.96 -764.99 -764.15 -763.88 -763.49
 9939.85 9948.99 9956.14 9959.46 9969.93 9972.01 9972.01 9980.40 9981.9610018.74
10022.2910023.5010031.6510031.6510032.7710043.2410053.7110057.1810064.1810074.66
10085.1310090.8610095.6010106.0710116.5410124.5310127.0210130.13
  249.30  246.84  244.90  243.94  241.41  240.93  240.93  238.97  238.68  233.71
  234.34  234.32  234.17  234.17  234.15  233.95  233.88  233.84  233.82  233.88
  233.96  233.89  233.71  234.04  235.01  235.85  236.12  236.51
 -750.70 -753.16 -755.10 -756.06 -758.59 -759.07  238.43  236.47  236.18  231.21
  231.84  231.82  231.67 -765.83 -765.85 -766.05 -766.12 -766.16 -766.18 -766.12
 -766.04 -766.11 -766.29 -765.96 -764.99 -764.15 -763.88 -763.49
Pier Skew, UpSta & Num, DnSta & Num=  ,9998.04, 2 ,10001.83, 2 , 0 , 0 , 0 ,,
    3.00    3.00
 -763.49  236.51
    3.00    3.00
 -764.00  236.00
BR Coef=-1 , 0 , 0 ,, 0 ,,,0.8,0,1,0,
WSPro=,,,, 1 ,,,, 0 ,,,, 0 ,,,,-1 ,-1 ,-1 , 0 , 0 , 0 , 0 , 0
BC Design=,, 0 ,, 0 ,,,,,,

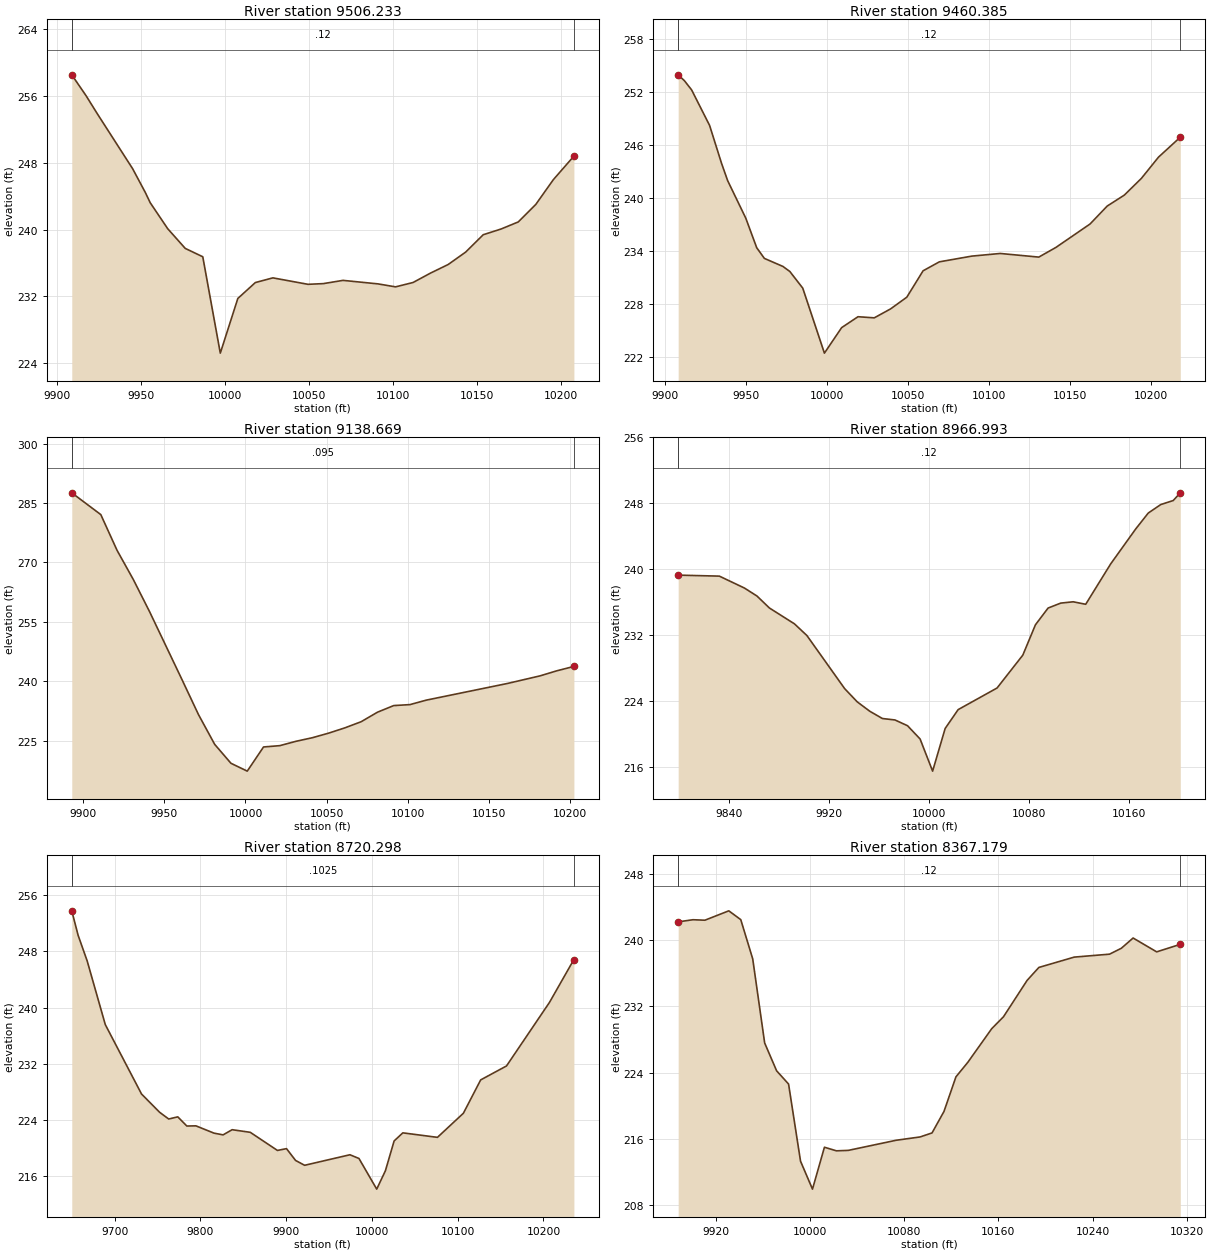
Type RM Length L Ch R = 1 ,9506.233,45.848600,45.848600,45.848600
XS GIS Cut Line= 2
 432579.74339503776037.397297949432293.264555282 775952.75582258
#Sta/Elev= 28
9909.035258.51249917.496256.02889924.409253.79759945.263 247.2719952.788244.4341
9955.691 243.2119966.118 240.0979976.545237.74219986.973236.7405  9997.4225.2094
10007.83 231.75310018.25233.653910028.68234.215610049.54 233.44410058.67233.5264
10070.39233.915510091.25233.494310101.67233.1387 10112.1233.662710122.53234.7942
10132.96235.813210143.38237.302510153.81 239.37610164.54240.070210174.66240.9083
10185.09243.004310195.52 245.96510207.76248.7852
#Mann= 3 , 0 , 0
9909.035    0.12       09909.035    0.12       010207.76    0.12       0
#XS Ineff= 2 , 0
       0                10019.71       0
Bank Sta=9909.035,10207.76
Exp/Cntr=0.3,0.1

Type RM Length L Ch R = 1 ,9460.385,321.715900,321.715900,321.715900
XS GIS Cut Line= 6
  432592.4335365776016.682508141432529.255289674775983.855563834
432515.947075754 775971.82945624432506.554731041775968.224916428
432422.990146935775968.727192923432302.239872604775930.985903972
#Sta/Elev= 30
  9908.3253.94929912.147253.28529916.566252.25429927.686248.2284 9935.01243.9684
9938.806241.99179950.008237.74169956.751234.39979961.474233.19399972.941232.2832
9977.189231.71289985.154229.83039998.509222.483510009.12225.363810019.21226.5989
10029.26226.4727 10039.3227.480610049.34228.809610059.38231.793510069.41232.8043
10089.44233.452110106.96233.751310130.74233.340510141.29234.432310162.39237.0868
10172.94239.110710183.49240.348210194.04 242.24110204.58244.640310218.04246.9003
#Mann= 3 , 0 , 0
  9908.3    0.12       0  9908.3    0.12       010218.04    0.12       0
#XS Ineff= 2 , 0
       0                               0
Bank Sta=9908.3,10218.04
Exp/Cntr=0.3,0.1

Type RM Length L Ch R = 1 ,9138.669,171.675600,171.675600,171.675600
XS GIS Cut Line= 2
 432662.84556374775846.114300117 432354.25181374775818.770550102
#Sta/Elev= 25
9892.839287.58099910.754282.08299920.793273.05719930.832265.68719940.872257.5602
 9960.95240.34929970.989231.62869981.028224.08629991.068219.311410001.11217.3357
10011.15223.432710021.19223.765310031.22 224.86910041.26 225.766 10051.3226.9205
10061.34228.257510071.38229.805810081.42232.204410091.46233.8782 10101.5234.1263
10111.54235.251910161.73239.468310181.81241.384710191.85242.628810202.64243.7673
#Mann= 3 , 0 , 0
9892.839   0.095       09892.839   0.095       010202.64   0.095       0
#XS Ineff= 2 , 0
       0                               0
Bank Sta=9892.839,10202.64
Exp/Cntr=0.3,0.1

Type RM Length L Ch R = 1 ,8966.993,246.695700,246.695700,246.695700
XS GIS Cut Line= 6
 432727.83735301775662.498600359 432620.14033457775658.161626894
432514.999108886775669.456042649432461.419284752775684.420775376
432428.035851752775689.596222135432329.353693103775688.302378364
#Sta/Elev= 30
9799.061239.2904 9832.01239.16919852.078237.72369862.097236.75669872.098235.2985
9892.099233.37859902.099231.95449932.285225.51369942.359223.90599952.432 222.763
9962.506221.8826 9972.58221.7073 9982.64221.00569992.663219.398610002.69215.4961
10012.73220.675510023.11222.961210054.26225.587910074.86229.573910084.98 233.262
 10095.1235.293310105.18235.891910115.19236.0536 10125.2235.750510145.21240.6587
10165.23244.897110175.24246.823210185.25 247.85610195.26 248.34810200.91249.2817
#Mann= 3 , 0 , 0
9799.061    0.12       09799.061    0.12       010200.91    0.12       0
#XS Ineff= 2 , 0
       0                               0
Bank Sta=9799.061,10200.91
Exp/Cntr=0.3,0.1

Type RM Length L Ch R = 1 ,8720.298,353.118600,353.118600,353.118600
XS GIS Cut Line= 6
432882.001748532775575.208391368432549.526528567775463.102328435
432511.290292233775456.388529226432429.172765434775445.706840768
432376.180280894775441.111119539432316.510728955775439.830984429
#Sta/Elev= 30
9650.094253.7846 9657.49250.30449668.054246.65119689.181237.58169731.435227.6977
9752.562225.09149763.126224.1381 9773.69224.44539784.253223.13829794.817223.1654
9815.944222.12499826.507221.88059837.071222.61549858.198222.24329889.889219.6623
9900.452219.91929911.016218.2367 9921.58217.54819974.397219.04779984.941218.5168
10005.62214.153410015.76216.772510025.91221.013210036.06222.166810076.42 221.526
10106.67224.960410126.82229.706710156.93231.693610207.01240.738910235.51246.8512
#Mann= 3 , 0 , 0
9650.094  0.1025       09650.094  0.1025       010235.51  0.1025       0
#XS Ineff= 2 , 0
       0                               0
Bank Sta=9650.094,10235.51
Exp/Cntr=0.3,0.1

Type RM Length L Ch R = 1 ,8367.179,163.339100,163.339100,163.339100
XS GIS Cut Line= 3
432807.348970741775362.534780279432550.143030256 775316.30325079
432384.932135731775324.706141621
#Sta/Elev= 30
9887.851242.23589900.398242.49379910.558242.43619930.878243.57129941.039 242.506
9951.199237.76249961.359227.5802 9971.52224.2136 9981.68222.6127 9991.84213.2802
   10002 209.89910012.16214.968410022.32 214.53310032.48214.587610073.12215.8114
10093.44216.2124 10103.6216.697610113.76219.299410123.92223.485610134.08225.2552
10154.33229.313210164.34230.756110184.37235.149810194.38236.720110224.42237.9707
10254.46238.327410264.47239.039210274.48240.281110294.51238.6072 10314.6 239.516
#Mann= 3 , 0 , 0
9887.851    0.12       09887.851    0.12       0 10314.6    0.12       0
#XS Ineff= 2 , 0
       0                               0
Bank Sta=9887.851,10314.6
Exp/Cntr=0.3,0.1

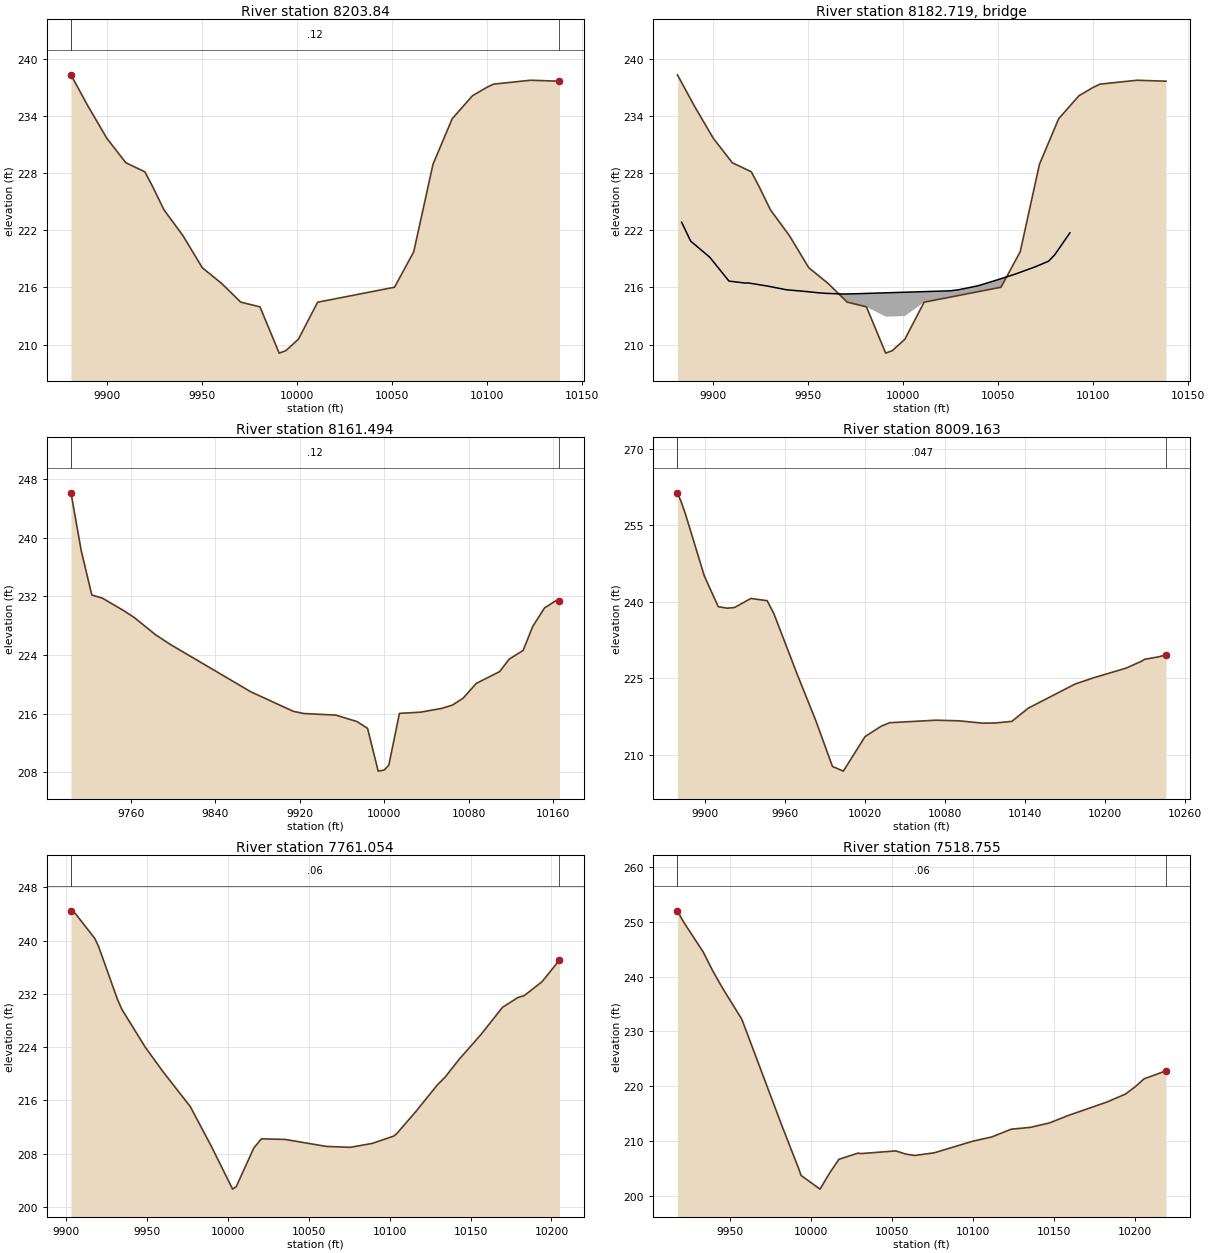
Type RM Length L Ch R = 1 , 8203.84,42.345500,42.345500,42.345500
XS GIS Cut Line= 4
432743.836239278775192.338020995432693.198585808775195.469917461
432540.420808047775219.081028581432493.716108382775241.635007501
#Sta/Elev= 25
9881.092238.31069889.945235.06529899.964231.65779909.983229.08679920.002228.1359
9924.214226.53789930.021224.16019940.122221.41659950.241218.0702 9960.36216.4341
9970.478214.46089980.597213.96729990.716209.11199994.223209.372410000.83210.5729
10010.95214.452910051.43216.025110061.55219.745710071.67 228.92110081.78   233.7
10092.44236.111610100.03236.999310103.54237.334110123.03 237.74110138.28237.6432
#Mann= 3 , 0 , 0
9881.092    0.12       09881.092    0.12       010138.28    0.12       0
#XS Ineff= 2 , 0
       09949.494        10039.05       0
Bank Sta=9881.092,10138.28
Exp/Cntr=0.3,0.1

Type RM Length L Ch R = 3 ,8182.719,,,
BEGIN DESCRIPTION:
END DESCRIPTION:
Bridge Culvert--1,0,-1,-1, 0
Deck Dist Width WeirC Skew NumUp NumDn MinLoCord MaxHiCord MaxSubmerge Is_Ogee
13.787750,14.770000,2.6,0, 27, 27, , , 0.95, 0, 0,0,,
 9883.32 9888.03 9898.12 9908.22 9916.96 9918.31 9928.40 9938.49 9948.59 9955.45
 9958.67 9968.73 9968.95 9974.56 9974.5610024.6710025.4410025.4410029.1010039.16
10049.2210056.0710059.3210069.4910076.5210079.6510087.72
  222.84  220.87  219.17  216.67  216.46  216.48  216.15  215.76  215.58  215.44
  215.39  215.31  215.31  215.34  215.34  215.65  215.67  215.67  215.76  216.17
  216.78  217.22  217.43  218.17  218.76  219.41  221.73
 -777.16 -779.13 -780.83 -783.33 -783.54 -783.52 -783.85 -784.24 -784.42 -784.56
 -784.61 -784.69 -784.69 -784.66  212.84  213.15  213.17 -784.33 -784.24 -783.83
 -783.22 -782.78 -782.57 -781.83 -781.24 -780.59 -778.27
 9883.32 9888.03 9898.12 9908.22 9916.96 9918.31 9928.40 9938.49 9948.59 9955.45
 9958.67 9968.73 9968.95 9974.56 9974.5610024.6710025.4410025.4410029.1010039.16
10049.2210056.0710059.3210069.4910076.5210079.6510087.72
  222.84  220.87  219.17  216.67  216.46  216.48  216.15  215.76  215.58  215.44
  215.39  215.31  215.31  215.34  215.34  215.65  215.67  215.67  215.76  216.17
  216.78  217.22  217.43  218.17  218.76  219.41  221.73
 -777.16 -779.13 -780.83 -783.33 -783.54 -783.52 -783.85 -784.24 -784.42 -784.56
 -784.61 -784.69 -784.69 -784.66  212.84  213.15  213.17 -784.33 -784.24 -783.83
 -783.22 -782.78 -782.57 -781.83 -781.24 -780.59 -778.27
BR Coef=-1 , 0 , 0 ,, 0 ,,,0.8,0,1,0,
WSPro=,,,, 1 ,,,, 0 ,,,, 0 ,,,,-1 ,-1 ,-1 , 0 , 0 , 0 , 0 , 0
BC Design=,, 0 ,, 0 ,,,,,,

Type RM Length L Ch R = 1 ,8161.494,152.331700,152.331700,152.331700
XS GIS Cut Line= 4
432914.669572592775136.088020995432669.587474704775159.358806372
432533.476363599775174.636584118432462.349321663775210.512065798
#Sta/Elev= 30
9703.318246.14749713.031238.25749723.076232.20079733.121231.77239753.211 230.074
9763.256229.13569783.346 226.7919797.599225.44349873.751218.98639913.931216.3285
9923.976216.02499954.119215.81249974.244214.93219984.307 214.003 9994.37208.1638
10000.08208.310510004.43  208.98 10014.5216.046910034.62216.211310054.75 216.732
10064.81217.185510074.87218.126910087.28 220.13610109.48221.753310118.36223.4364
10131.69 224.64310140.76227.910610151.96230.441810163.16231.459710166.13231.3592
#Mann= 3 , 0 , 0
9703.318    0.12       09703.318    0.12       010166.13    0.12       0
#XS Ineff= 2 , 0
       09952.188        10025.36       0
Bank Sta=9703.318,10166.13
Exp/Cntr=0.3,0.1

Type RM Length L Ch R = 1 ,8009.163,248.109100,248.109100,248.109100
XS GIS Cut Line= 2
432720.022581846774983.368113592432420.543415189775194.305613592
#Sta/Elev= 30
9879.346261.3507 9882.18259.58959885.489  257.099899.546245.04479909.952239.0472
9916.911238.75129922.184238.89249934.416240.66349946.647240.21969951.643 237.698
9969.009225.90369983.342216.57579995.573207.758810003.74 206.83810020.04213.6051
10032.27  215.6610038.47216.3209 10073.2216.813310090.57216.693210107.93216.2409
10117.89216.270510130.12216.588510142.35219.1579 10177.4223.879210191.28 225.111
10215.74 227.00810227.97228.4438 10229.5228.7332 10240.2229.223910245.66229.6345
#Mann= 3 , 0 , 0
9879.346   0.047       09879.346   0.047       010245.66   0.047       0
#XS Ineff= 2 , 0
       0                               0
Bank Sta=9879.346,10245.66
Exp/Cntr=0.3,0.1

Type RM Length L Ch R = 1 ,7761.054,242.299000,242.299000,242.299000
XS GIS Cut Line= 6
432516.890371607774934.405817629432471.128551567774981.641255714
432423.742145253  775021.4161422432408.786551921775040.530472065
432399.821669406 775051.50497356432298.782529882775142.203846255
#Sta/Elev= 30
9903.128244.47789905.845244.06989917.878240.32369920.216239.11359931.802231.2117
9934.588229.6683 9948.96224.01969959.648220.42019976.896215.04519989.674209.1817
10003.01202.656710005.23203.022510016.06208.814610020.78210.213410035.34 210.127
10060.81209.079310075.69208.937710089.41209.534510102.56210.627310104.38210.9832
   10116214.248310129.44218.293110134.32219.482510142.88 222.13610156.32225.8466
10169.75229.969910179.23231.443910183.19231.7312 10194.2233.827210204.99 237.078
#Mann= 3 , 0 , 0
9903.128    0.06       09903.128    0.06       010204.99    0.06       0
#XS Ineff= 2 , 0
       0                10063.63       0
Bank Sta=9903.128,10204.99
Exp/Cntr=0.3,0.1

Type RM Length L Ch R = 1 ,7518.755,272.432100,272.432100,272.432100
XS GIS Cut Line= 6
432407.359392154774791.914453457432368.225417222 774848.44168056
432330.548802054774910.414854275432324.589169389774919.298582149
432267.877160756775007.792394151432245.548225781775046.720421363
#Sta/Elev= 30
9917.356 251.9829921.109249.96699933.271244.49339939.069241.09939945.434237.7908
9956.637232.47229957.596231.88019981.922212.81299992.316204.97229993.783203.7358
10005.49201.240310011.57204.235710017.19206.677810028.89207.803910030.82207.7199
 10052.3 208.20810058.63207.620410064.12207.378810076.11207.861410099.86209.9726
10111.74210.758310123.62212.163910135.49212.499310147.37213.312210159.25214.7035
10182.75217.108610194.28218.571510200.32219.908210205.81  221.3610219.32222.8033
#Mann= 3 , 0 , 0
9917.356    0.06       09917.356    0.06       010219.32    0.06       0
#XS Ineff= 2 , 0
       0                               0
Bank Sta=9917.356,10219.32
Exp/Cntr=0.3,0.1