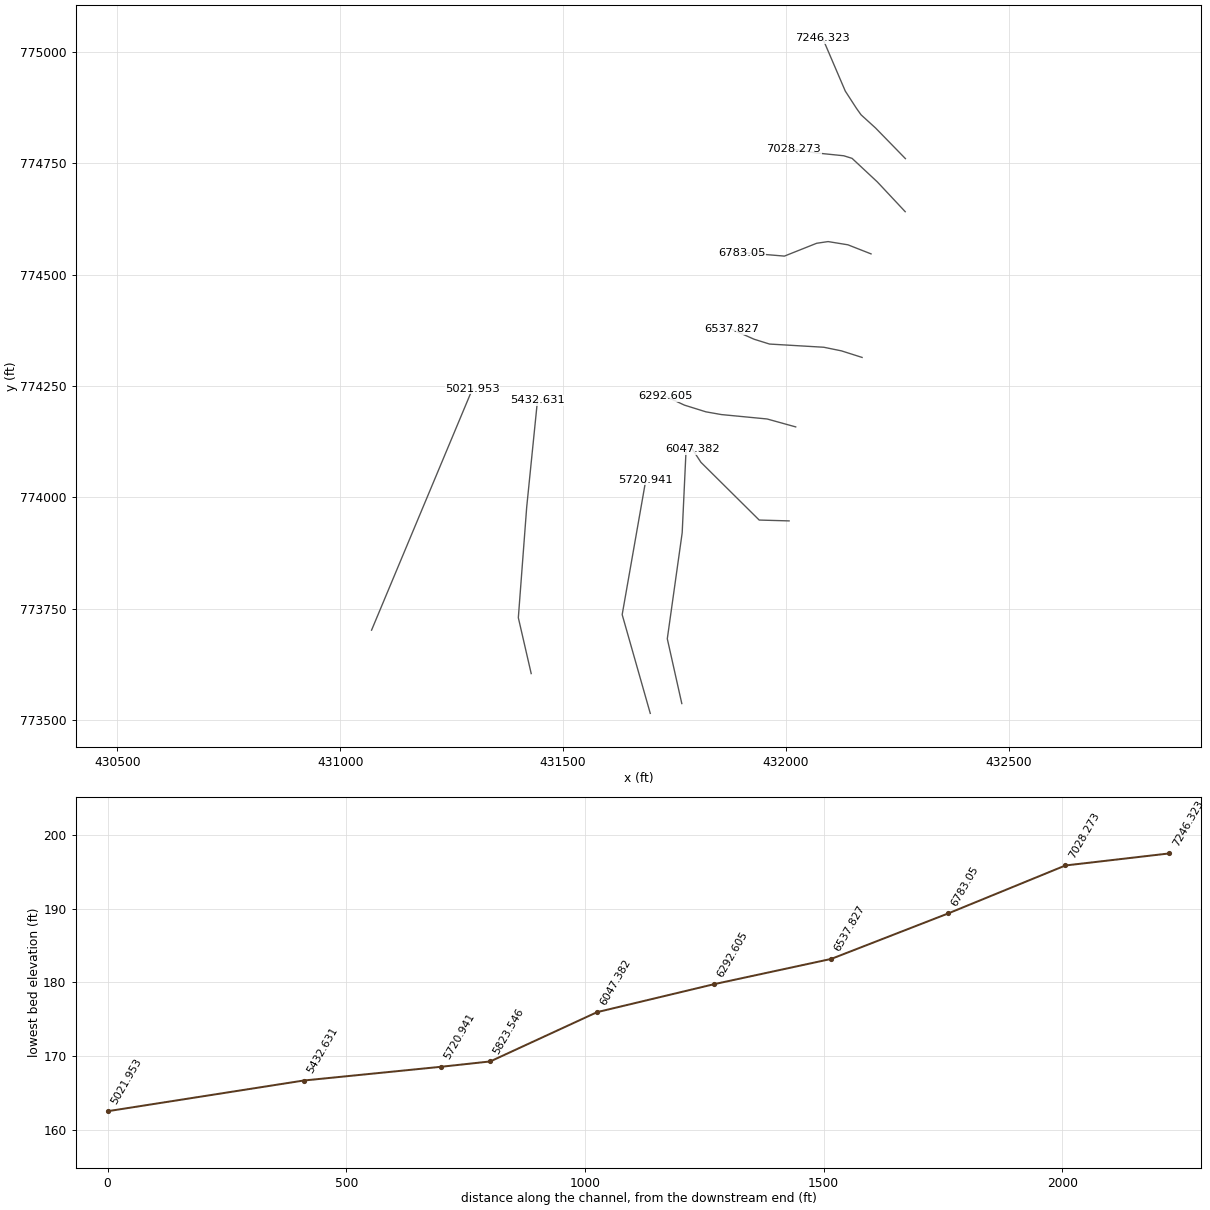
HEC-RAS study 2986_ras.prj: 2986

--- 2986_ras.g01 (geometry) --- (continued)

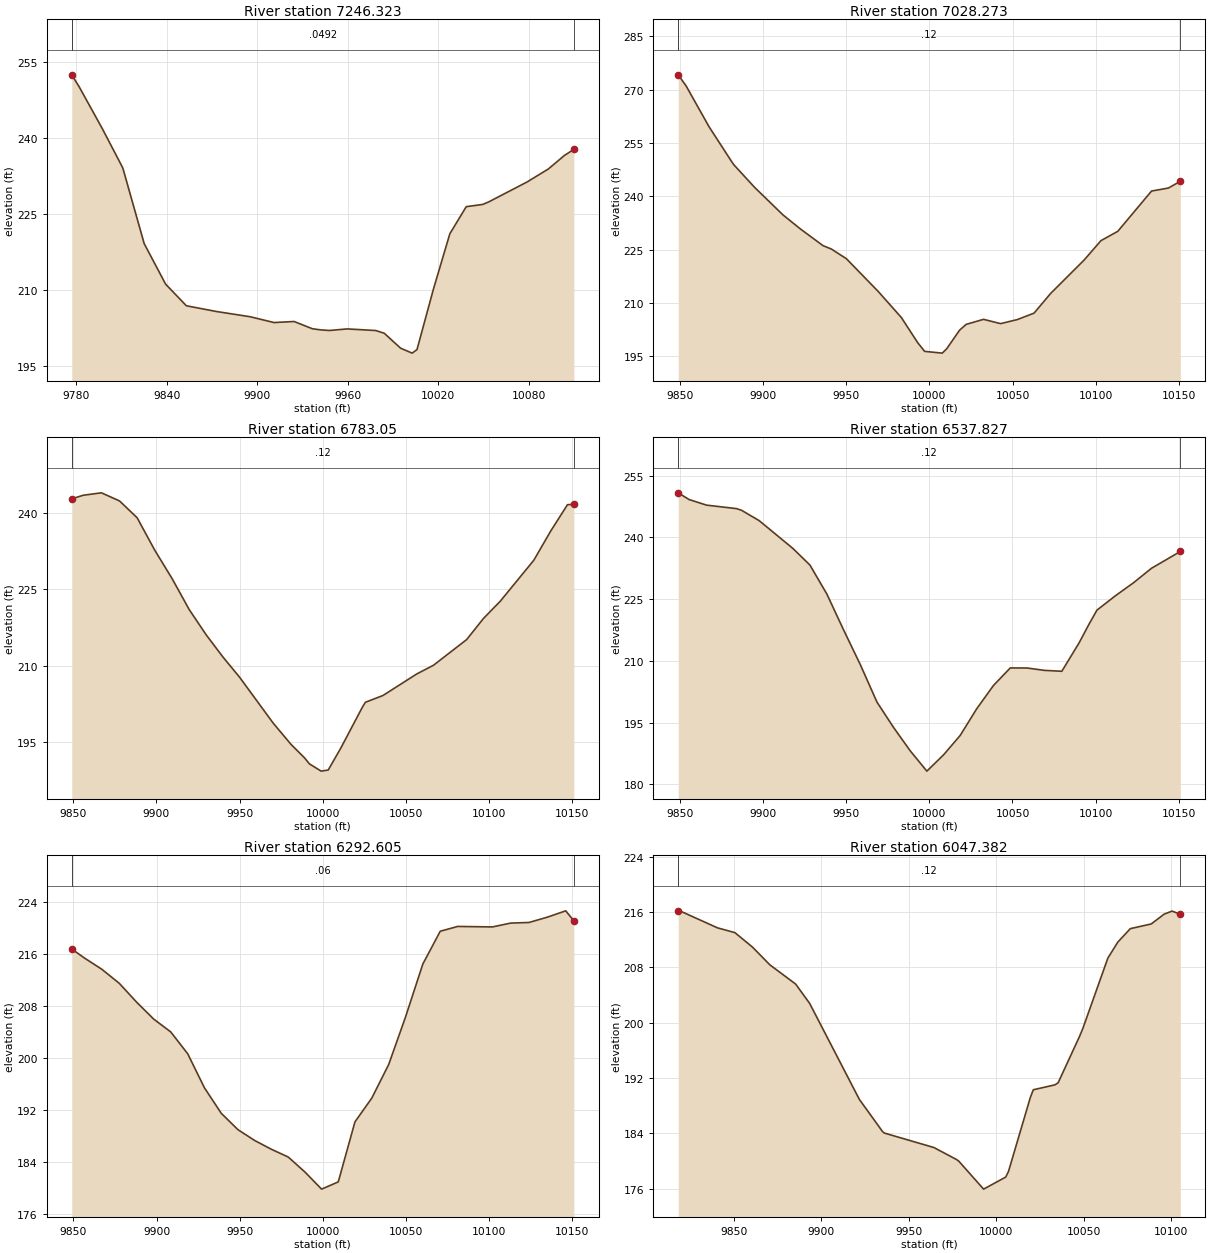
Type RM Length L Ch R = 1 ,7246.323,218.050000,218.050000,218.050000
XS GIS Cut Line= 6
 432268.45898968774760.610827893432201.337548167774829.418800503
 432168.93339774774858.910244554432158.593330681774873.432956144
432133.548688799774912.086522341 432082.76743874775030.576105654
#Sta/Elev= 30
 9776.99252.39249781.944250.00829797.091241.86539810.585234.17519811.061233.7854
9825.031219.09139839.227211.11469852.971206.85579873.114205.71449895.205204.6964
 9911.12 203.5479924.405 203.7569936.532202.32459942.411202.08889947.857201.9852
9959.596202.29199978.531 201.9749984.121201.4482    9995198.494110002.65197.5186
10005.88198.218110016.76210.126310027.64221.046110038.52 226.396 10049.4226.8336
10053.42227.335610078.81231.256810092.92233.8211 10103.8236.538610109.86237.6796
#Mann= 3 , 0 , 0
 9776.99  0.0492       0 9776.99  0.0492       010109.86  0.0492       0
#XS Ineff= 2 , 0
       09928.578                       0
Bank Sta=9776.99,10109.86
Exp/Cntr=0.3,0.1

Type RM Length L Ch R = 1 ,7028.273,245.222600,245.222600,245.222600
XS GIS Cut Line= 6
 432268.00133788774641.511040576432205.424674749774708.316362296
432148.754803255774761.168794708432130.086921587774767.001552129
 432065.90144183774773.600237799432017.936662098774781.526917324
#Sta/Elev= 30
9849.008274.16879853.788271.0216 9867.49259.59929881.192249.70689882.653248.7564
9894.894242.52539911.909234.79399922.297230.86999935.999226.12759941.138225.1419
9950.093222.4465 9969.14213.2763 9983.14205.90199992.956198.83219997.141196.3726
10007.73 195.878 10010.4197.101610018.15202.328110022.08203.963610032.56205.3824
10042.82204.177410052.87205.314910062.93207.132410072.98212.715310093.08222.0934
10103.14227.519310113.28230.154910133.55241.472710143.69242.316610150.85244.2215
#Mann= 3 , 0 , 0
9849.008    0.12       09849.008    0.12       010150.85    0.12       0
#XS Ineff= 2 , 0
       0                               0
Bank Sta=9849.008,10150.85
Exp/Cntr=0.3,0.1

Type RM Length L Ch R = 1 , 6783.05,245.222600,245.222600,245.222600
XS GIS Cut Line= 6
  432191.3070623774546.785610651432139.347938474774567.158482044
 432094.98234683774574.391795994432069.210642531774570.594247235
431996.874524149774541.802712992431901.208854717774549.796167693
#Sta/Elev= 30
9849.132242.7697 9856.02243.47299866.941243.94819877.862 242.3549888.439239.0501
9899.013232.69639909.455227.11189919.726221.05099929.938216.08849939.982211.7531
9950.027207.77259970.244198.76299980.854194.6318 9989.04191.9632 9991.96190.7946
    9999189.372610003.24189.584710010.97193.981710023.85201.957310025.61 202.876
10036.13204.198610056.48 208.43310066.48210.127510086.48215.179110096.52219.3014
10106.62222.683510126.82230.737710136.93236.434110147.03 241.61910150.86241.6951
#Mann= 3 , 0 , 0
9849.132    0.12       09849.132    0.12       010150.86    0.12       0
#XS Ineff= 2 , 0
       0                               0
Bank Sta=9849.132,10150.86
Exp/Cntr=0.3,0.1

Type RM Length L Ch R = 1 ,6537.827,245.222500,245.222500,245.222500
XS GIS Cut Line= 6
432171.261957283774314.374634146432124.917434405774329.103370449
432085.285076358774337.222495553431963.493102386774344.398038408
431928.948000747774355.185406651431879.182319049774377.227985548
#Sta/Elev= 30
9849.055250.81069855.626249.17039866.119247.81879884.136246.97119887.105246.5688
9897.684 244.0679918.015237.29029928.223233.27299938.426226.21199948.464217.5096
9958.502209.0943 9968.54199.96669978.543 193.7889988.543188.12489998.544183.1904
10008.55187.133810018.55191.847810028.55198.363310038.59203.998810048.69208.2656
10058.78208.2458 10069.2207.673210079.68207.453510090.15214.408910095.87218.7755
10100.81222.311810111.75225.751910122.69228.930410133.62232.484610150.92236.5563
#Mann= 3 , 0 , 0
9849.055    0.12       09849.055    0.12       010150.92    0.12       0
#XS Ineff= 2 , 0
       0                               0
Bank Sta=9849.055,10150.92
Exp/Cntr=0.3,0.1

Type RM Length L Ch R = 1 ,6292.605,245.222600,245.222600,245.222600
XS GIS Cut Line= 6
 432022.20710653774158.447825261431958.015338732774176.231150417
431855.489297175774186.124551989431820.612807677774192.294113904
431772.432670754774207.309185236431730.581063209774226.926362877
#Sta/Elev= 30
9849.045216.73539856.618 215.3629867.127213.61959877.636 211.4519888.053208.5482
9898.306205.94889908.559203.97039918.758200.60639928.828195.35839938.899191.4457
 9948.97188.9162 9959.04187.24779969.111185.89359979.181184.70389989.239 182.395
9999.244179.761810009.26180.875910019.29 190.11410029.44193.7873 10039.6198.9652
10049.75206.307810060.09214.418710070.56 219.47310081.04220.214810101.98220.1406
10112.88220.730810123.93220.826310134.97221.643610146.01222.620210150.89221.0824
#Mann= 3 , 0 , 0
9849.045    0.06       09849.045    0.06       010150.89    0.06       0
#XS Ineff= 2 , 0
       0                               0
Bank Sta=9849.045,10150.89
Exp/Cntr=0.3,0.1

Type RM Length L Ch R = 1 ,6047.382,223.836000,223.836000,223.836000
XS GIS Cut Line= 4
432007.399607331773947.481250167431940.289610654773949.363435373
431809.482940644774078.991666839431789.951690644774108.939583495
#Sta/Elev= 30
9818.202216.16699820.602215.9928 9840.61213.71099850.614 213.0169860.618210.9337
9870.622208.35779885.338205.58559893.346202.79079921.759188.92429935.021 184.276
9935.965184.06749964.379181.97089977.257 180.2469978.585180.00859992.792 175.961
10005.41177.6979   10007   178.510019.49189.1843 10021.2190.315910033.57191.0245
10035.41191.330610047.65198.030510049.62199.235410063.82209.3325 10069.5211.6388
10076.67213.593310088.61 214.26810096.01215.685310100.55216.128810105.25215.6699
#Mann= 3 , 0 , 0
9818.202    0.12       09818.202    0.12       010105.25    0.12       0
#XS Ineff= 2 , 0
       0                               0
Bank Sta=9818.202,10105.25
Exp/Cntr=0.3,0.1

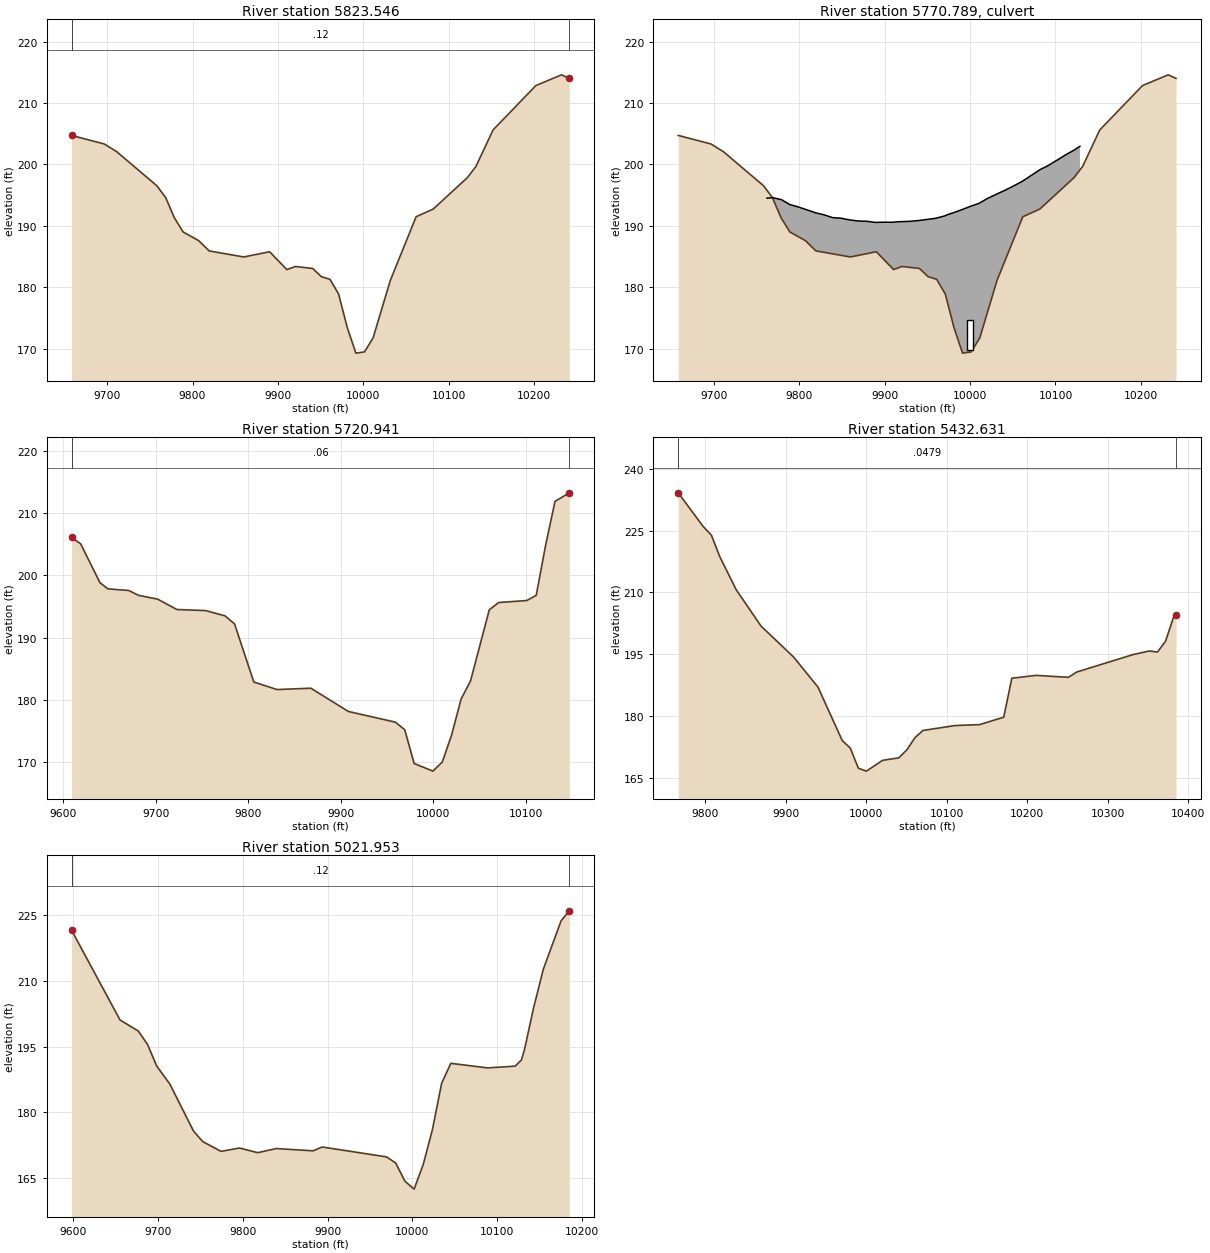
Type RM Length L Ch R = 1 ,5823.546,102.605300,102.605300,102.605300
XS GIS Cut Line= 4
 431766.56178987773537.495965555431734.009706557773682.895271108
431767.426788658773920.743524507431776.499317378774114.180394381
#Sta/Elev= 30
9658.327204.7257 9696.76203.32659711.248202.07449758.245196.52239768.492194.6154
 9778.74191.29789788.987189.00659807.326187.57119819.549185.91269859.942184.9303
9890.237185.77939910.433182.87569920.532 183.3799940.728183.05689950.826181.7225
9960.924  181.299971.023178.88839981.121173.45379991.219169.268610001.32169.4674
10011.42171.750410031.61181.121610061.78191.4808 10081.8192.735310121.85197.8621
10131.86199.680110151.88205.618110201.94212.840610231.97214.594510241.16214.0254
#Mann= 3 , 0 , 0
9658.327    0.12       09658.327    0.12       010241.16    0.12       0
#XS Ineff= 2 , 0
       09904.118        10064.44       0
Bank Sta=9658.327,10241.16
Exp/Cntr=0.3,0.1

Type RM Length L Ch R = 2 ,5770.789,,,
Bridge Culvert--1,0,-1,-1, 0
Deck Dist Width WeirC Skew NumUp NumDn MinLoCord MaxHiCord MaxSubmerge Is_Ogee
22.803,57,2.6,0,44,44, , , 0.95, 0, 0,0,,
 9762.19 9769.02 9779.03 9789.04 9799.04 9809.05 9819.05 9829.06 9839.06 9849.07
 9859.08 9869.08 9879.09 9889.09 9899.10 9909.11 9912.43 9914.28 9919.20 9929.34
 9939.48 9949.62 9959.76 9969.90 9974.58 9980.04 9990.1910000.3310010.4710020.61
10030.7510034.8810040.8910051.0310061.1710071.3110081.4510085.0210091.5710096.58
10101.6810111.7810121.8910128.64
  194.51  194.59  194.27  193.46  193.07  192.60  192.13  191.79  191.34  191.24
  190.96  190.79  190.74  190.56  190.59  190.58  190.62  190.66  190.68  190.73
  190.86  191.04  191.23  191.60  191.87  192.11  192.62  193.17  193.66  194.48
  195.14  195.41  195.79  196.50  197.25  198.18  199.11  199.37  199.82  200.26
  200.68  201.55  202.34  202.95
                                                                                
                                                                                
                                                                                
                                                                                
                                
 9762.19 9769.02 9779.03 9789.04 9799.04 9809.05 9819.05 9829.06 9839.06 9849.07
 9859.08 9869.08 9879.09 9889.09 9899.10 9909.11 9912.43 9914.28 9919.20 9929.34
 9939.48 9949.62 9959.76 9969.90 9974.58 9980.04 9990.1910000.3310010.4710020.61
10030.7510034.8810040.8910051.0310061.1710071.3110081.4510085.0210091.5710096.58
10101.6810111.7810121.8910128.64
  194.51  194.59  194.27  193.46  193.07  192.60  192.13  191.79  191.34  191.24
  190.96  190.79  190.74  190.56  190.59  190.58  190.62  190.66  190.68  190.73
  190.86  191.04  191.23  191.60  191.87  192.11  192.62  193.17  193.66  194.48
  195.14  195.41  195.79  196.50  197.25  198.18  199.11  199.37  199.82  200.26
  200.68  201.55  202.34  202.95
                                                                                
                                                                                
                                                                                
                                                                                
                                
BR Coef=-1 , 0 , 0 ,, 0 ,,,0.8,-1,,0,
WSPro=,,,, 1 ,,,, 0 ,,,, 0 ,,,,-1 ,-1 ,-1 , 0 , 0 , 0 , 0 , 0
Culvert=2,5,8,57,0.013,0.4,1,8,1,169.72,10000,169.09,10000,Culvert #1, 0, 22.803
Culvert Bottom n=0.013
BC Design=,, 0 ,, 0 ,,,,,,

Type RM Length L Ch R = 1 ,5720.941,288.310300,288.310300,288.310300
XS GIS Cut Line= 3
431695.779361293773515.461862015431632.749317288773737.097061023
431685.947159222774040.240319044
#Sta/Elev= 30
9609.103 206.0999619.019 205.0389639.812198.8118 9648.51197.81979671.002197.5595
9681.398196.78599702.191196.16919722.984194.50499754.174194.32819774.967193.4915
9785.364192.18849806.157182.85479831.298181.64869867.856181.86339908.467178.1241
9959.231176.41139969.384175.19399979.537169.76789999.842168.5455   10010170.0197
10020.15174.4074 10030.3180.125710040.45183.012210060.76194.454910070.91195.6279
10101.37195.948510111.52196.779610121.68204.823310131.83211.8754 10147.3 213.246
#Mann= 3 , 0 , 0
9609.103    0.06       09609.103    0.06       0 10147.3    0.06       0
#XS Ineff= 2 , 0
       09902.884                       0
Bank Sta=9609.103,10147.3
Exp/Cntr=0.3,0.1

Type RM Length L Ch R = 1 ,5432.631,410.677400,410.677400,410.677400
XS GIS Cut Line= 4
431428.532566607773604.800991997431399.667148054773730.137677833
431418.417148054 773978.05434452431442.654093087  774217.8923776
#Sta/Elev= 30
9766.596234.17039797.585226.00179807.847223.86539818.109218.72819838.632210.6593
9869.418201.86129910.118194.29359940.204187.0386 9970.29 174.1029980.318172.2557
9990.347167.380510000.38166.675510020.43 169.29910040.49169.885810050.52171.8249
10060.55174.777810070.58176.535210110.69177.737710140.78177.946510170.92179.7518
10180.97189.208810211.12189.898710251.33189.424810261.38190.699510331.74194.9515
10351.84 195.81410361.89195.557710371.94198.193110381.99204.1048 10384.9204.5261
#Mann= 3 , 0 , 0
9766.596  0.0479       09766.596  0.0479       0 10384.9  0.0479       0
#XS Ineff= 2 , 0
       0                               0
Bank Sta=9766.596,10384.9
Exp/Cntr=0.3,0.1

Type RM Length L Ch R = 1 ,5021.953,0.000000,0.000000,0.000000
XS GIS Cut Line= 2
431070.258259743773702.267377585431296.820759743774243.934044272
#Sta/Elev= 30
9597.908221.55569655.067201.08949676.746198.54239687.586 195.4679698.425190.5606
9713.856186.46259741.783175.75449752.623173.34759774.302171.11559795.981171.8854
9817.517 170.8179839.339171.76119882.697171.24049893.536172.11459969.413 169.862
9980.252 168.4689991.092164.329610001.93162.506810012.77168.140510023.61176.1071
10034.45186.637910045.29191.197210088.65190.152310121.17190.5517 10128.5191.9553
10132.01194.176810142.84203.785910154.41212.668110175.36 223.69610185.05225.9711
#Mann= 3 , 0 , 0
9597.908    0.12       09597.908    0.12       010185.05    0.12       0
#XS Ineff= 2 , 0
       0                               0
Bank Sta=9597.908,10185.05
Exp/Cntr=0.3,0.1